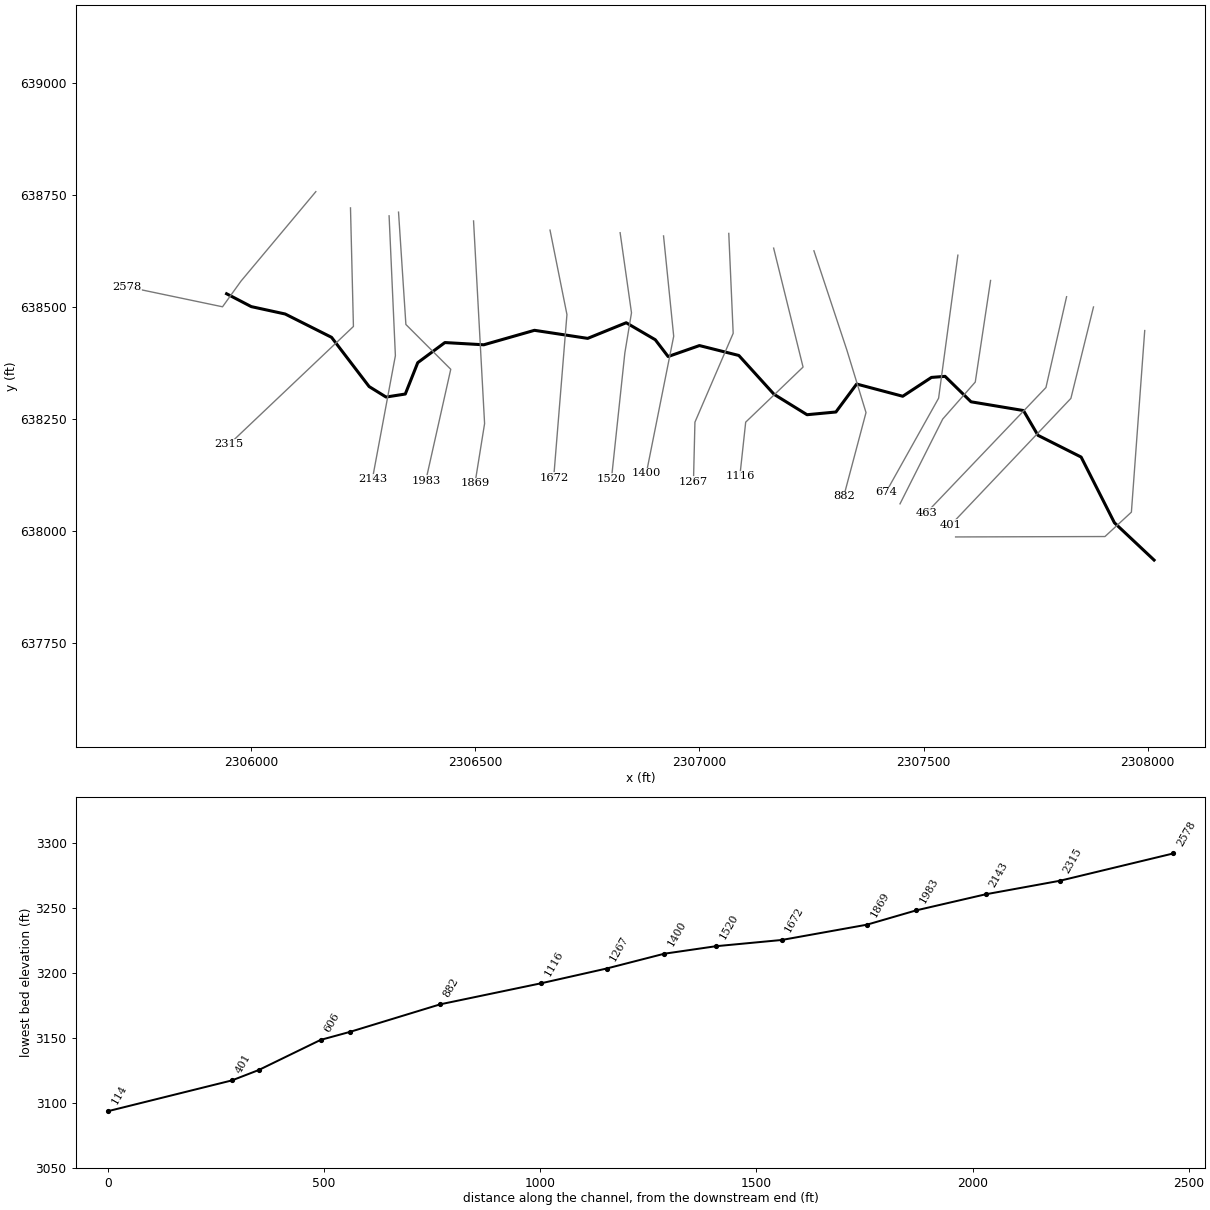
--- STALNAKRN4.prj (project) ---

Proj Title=STALNAKRN4
Current Plan=p01
Default Exp/Contr=0,0
English Units
Geom File=g01
Flow File=f01
Plan File=p01
BEGIN DESCRIPTION:
----------MODEL BY WOOD PLC 2022----------
AFH study
Randolph County, WV
HEC-RAS Version: RAS 6.2
Vertical Datum: NAVD88
Projection: NAD 1983 StatePlane West Virginia S FIPS 4702 (US Feet)
Terrain: 1-meter LIDAR (FEMA Region III 3DEP collected 2016-2018)
Land Use: 2019 NLCD
Hydrologic Method:
WV SIR2010-5033 regression equations
Additional Model Notes:
None
END DESCRIPTION:
DSS Export Rating Curves= 0
DSS Export Rating Curve Sorted= 0
DSS Export Volume Flow Curves= 0
DXF OffsetX= 0
DXF OffsetY= 0
DXF ScaleX= 0
DXF ScaleY= 0

--- STALNAKRN4.p01 (plan) ---

Plan Title=Floodplain
Program Version=6.20
Short Identifier=Floodplain
Geom File=g01
Flow File=f01
Subcritical Flow
K Sum by GR= 0
Std Step Tol= 0.01
Critical Tol= 0.01
Num of Std Step Trials= 20
Max Error Tol= 0.3
Flow Tol Ratio= 0.001
Split Flow NTrial= 30
Split Flow Tol= 0.02
Split Flow Ratio= 0.02
Log Output Level= 0
Friction Slope Method= 1
Unsteady Friction Slope Method= 2
Unsteady Bridges Friction Slope Method= 1
Parabolic Critical Depth
Global Vel Dist= 0 , 0 , 0
Global Log Level= 0
CheckData=True
Encroach Param=-1 ,0,0, 0
Mapping Interval=1HOUR
Computation Time Step Use Courant=        0
Computation Time Step Use Time Series=    0
Computation Time Step Count To Double=0
Computation Time Step Max Doubling=0
Computation Time Step Max Halving=0
Computation Time Step Residence Courant=0
Run HTab= 0
Run UNet= 0
Run Sediment= 0
Run PostProcess= 0
Run WQNet= 0
Run RASMapper=-1
UNET Theta= 0
UNET Theta Warmup= 0
UNET ZTol= 0
UNET ZSATol= 0
UNET MxIter= 0
UNET Max Iter WO Improvement= 0
UNET MaxInSteps= 0
UNET DtIC= 0
UNET DtMin= 0
UNET MaxCRTS= 0
UNET WFStab= 0
UNET SFStab= 0
UNET WFX= 1
UNET SFX= 1
UNET Gravity=32.174
UNET 1D Methodology=Finite Difference
UNET DSS MLevel= 1
UNET Pardiso=0
UNET DZMax Abort= 0
UNET Use Existing IB Tables= 0
UNET Froude Reduction=False
UNET Froude Limit= 0
UNET Froude Power= 0
UNET D1 Cores= 0
UNET WindReference=Eulerian
UNET WindDragFormulation=Hsu (1988)
UNET D2 Coriolis=0
UNET D2 Cores= 0
UNET D2 Theta= 1
UNET D2 Theta Warmup= 1
UNET D2 Z Tol= 0.01
UNET D2 Volume Tol= 0.01
UNET D2 Max Iterations= 20
UNET D2 Equation= 0
UNET D2 RampUpFraction=0.1
UNET D2 TimeSlices= 1
UNET D2 Turbulence Formulation=Non-Conservative (original)
UNET D2 Eddy Viscosity=0.3
UNET D2 Transverse Eddy Viscosity=0.1
UNET D2 Smagorinsky Mixing=0
UNET D2 BCVolumeCheck=0
UNET D2 Cores=0
UNET D2 SolverType=PARDISO (Direct)
UNET D2 Minimum Iterations= 2147483647
UNET D2 Maximum Iterations= 2147483647
UNET D2 Restart Number= 10
UNET D2 Relaxation Coeff=1.3
UNET D2 SOR Precondition Iterations= 10
UNET D2 ILUT Maximum Fill= 8
UNET D2 ILUT Tolerance=1E-08
UNET D1D2 MaxIter= 0
UNET D1D2 ZTol=0.01
UNET D1D2 QTol=0.1
UNET D1D2 MinQTol=1
Write IC File= 0
Write IC File at Fixed DateTime=0
Write IC File at Sim End=0
Echo Input=False
Echo Parameters=False
Echo Output=False
Write Detailed= 0
HDF Write Warmup=0
HDF Write Time Slices=0
HDF Flush=0
HDF Compression= 1
HDF Chunk Size= 1
HDF Spatial Parts= 1
HDF Use Max Rows=0
HDF Fixed Rows= 1
Calibration Method= 0
Calibration Iterations= 20
Calibration Max Change=0.05
Calibration Tolerance=0.2
Calibration Maximum=1.5
Calibration Minimum=0.5
Calibration Optimization Method= 1
WQ AD Non Conservative
WQ ULTIMATE=-1
WQ Max Comp Step=1HOUR
WQ Output Interval=15MIN
WQ Output Selected Increments= 0
WQ Output face flow=0
WQ Output face velocity=0
WQ Output face area=0
WQ Output face dispersion=0
WQ Output cell volume=0
WQ Output cell surface area=0
WQ Output cell continuity=0
WQ Output cumulative cell continuity=0
WQ Output face conc=0
WQ Output face dconc_dx=0
WQ Output face courant=0
WQ Output face peclet=0
WQ Output face adv mass=0
WQ Output face disp mass=0
WQ Output cell mass=0
WQ Output cell source sink temp=0
WQ Output nsm pathways=0
WQ Output nsm derived pathways=0
WQ Create Restart=0
WQ Fixed Restart=0
WQ System Summary=0
WQ Write To DSS=0
Sorting and Armoring Iterations= 10
XS Update Threshold= 0.02
Bed Roughness Predictor= 0
Hydraulics Update Threshold= 0.02
Energy Slope Method= 1
Volume Change Method= 1
Sediment Retention Method= 0
Sediment TS Multiplier= 1
Warm Up Method= 0
XS Weighting Method= 0
Number of US Weighted Cross Sections= 1
Number of DS Weighted Cross Sections= 1
Upstream XS Weight=0
Main XS Weight=1
Downstream XS Weight=0
Number of DS XS's Weighted with US Boundary= 1
Upstream Boundary Weight= 1
Weight of XSs Associated with US Boundary= 0
Number of US XS's Weighted with DS Boundary= 1
Downstream Boundary Weight= 0.5
Weight of XSs Associated with DS Boundary= 0.5
Percentile Method= 0
Sediment Output Level= 3
Mass or Volume Output= 0
Output Increment Type= 1
Profile and TS Output Increment= 1
Transport Output Increment 1
XS Output Flag= 0
XS Output Increment= 10
Read HDF5 Sediment Hotstart= 0
Sediment Hotstart Type= 0
Write Gradation File= 0
Read Gradation Hotstart= 0
Write HDF5 File= 1
Write Binary Output= 1
Write DSS Sediment File= 0
DSS Sediment Output Type= 1
SV Curve= 0
Specific Gage Flag= 0
Subcell Erosion Methods= 0
Subcell Deposition Methods= 0
Advection Scheme= 1
Matrix Solver= 0
Implicit Weighting Factor= 1
Maximum Outer Loop Convergence Iterations= 5
Convergence Maximum Absolute= 0.001
Convergence RMSE= 0.0001
Grain Fractions Max Abs Error= 0.001
Max Subgrid Regions= 1
Max Subgrid Length Scale= 3.402823E+38
Initial Layer Thickness= 3.402823E+38
Min Layer Thickness= 3.402823E+38
Max Layer Thickness= 3.402823E+38
Number of Layers= 5

--- STALNAKRN4.f01 (steady flow) ---

Flow Title=Flow
Program Version=6.20
Number of Profiles= 1
Profile Names=P100yr
River Rch & RM=STALNAKRN4,Main,2578
     376
Boundary for River Rch & Prof#=STALNAKRN4,Main            , 1
Up Type= 0
Dn Type= 3
Dn Slope=0.09775
DSS Import GetInterval= 0
DSS Import GetPeak= 0
DSS Import FillOption= 0

--- STALNAKRN4.g01 (geometry) ---

Geom Title=Geometry
Program Version=6.20

River Reach=STALNAKRN4      ,Main
Reach XY= 30
2305944.92280454638529.5108158012305999.99697716638500.785592417
     2306075.639      638484.272  2306179.102119638432.158593385
     2306262.914      638322.163     2306300.674      638298.725
     2306343.643      638305.453      2306371.42      638375.548
     2306431.967       638420.47     2306518.773      638415.479
     2306631.837      638447.814     2306750.544      638429.802
     2306836.481      638464.741     2306901.368      638426.764
     2306930.014       638389.22     2306999.893      638413.743
     2307087.783      638391.607     2307166.342      638304.802
      2307239.91      638259.229     2307304.363      638265.306
     2307350.587      638327.805     2307453.452      638300.462
     2307517.471      638342.562     2307547.853      638344.949
     2307605.795      638288.092     2307722.766       638268.56
     2307755.101      638213.222     2307851.455      638164.611
     2307925.761      638017.736     2308014.165      637934.465

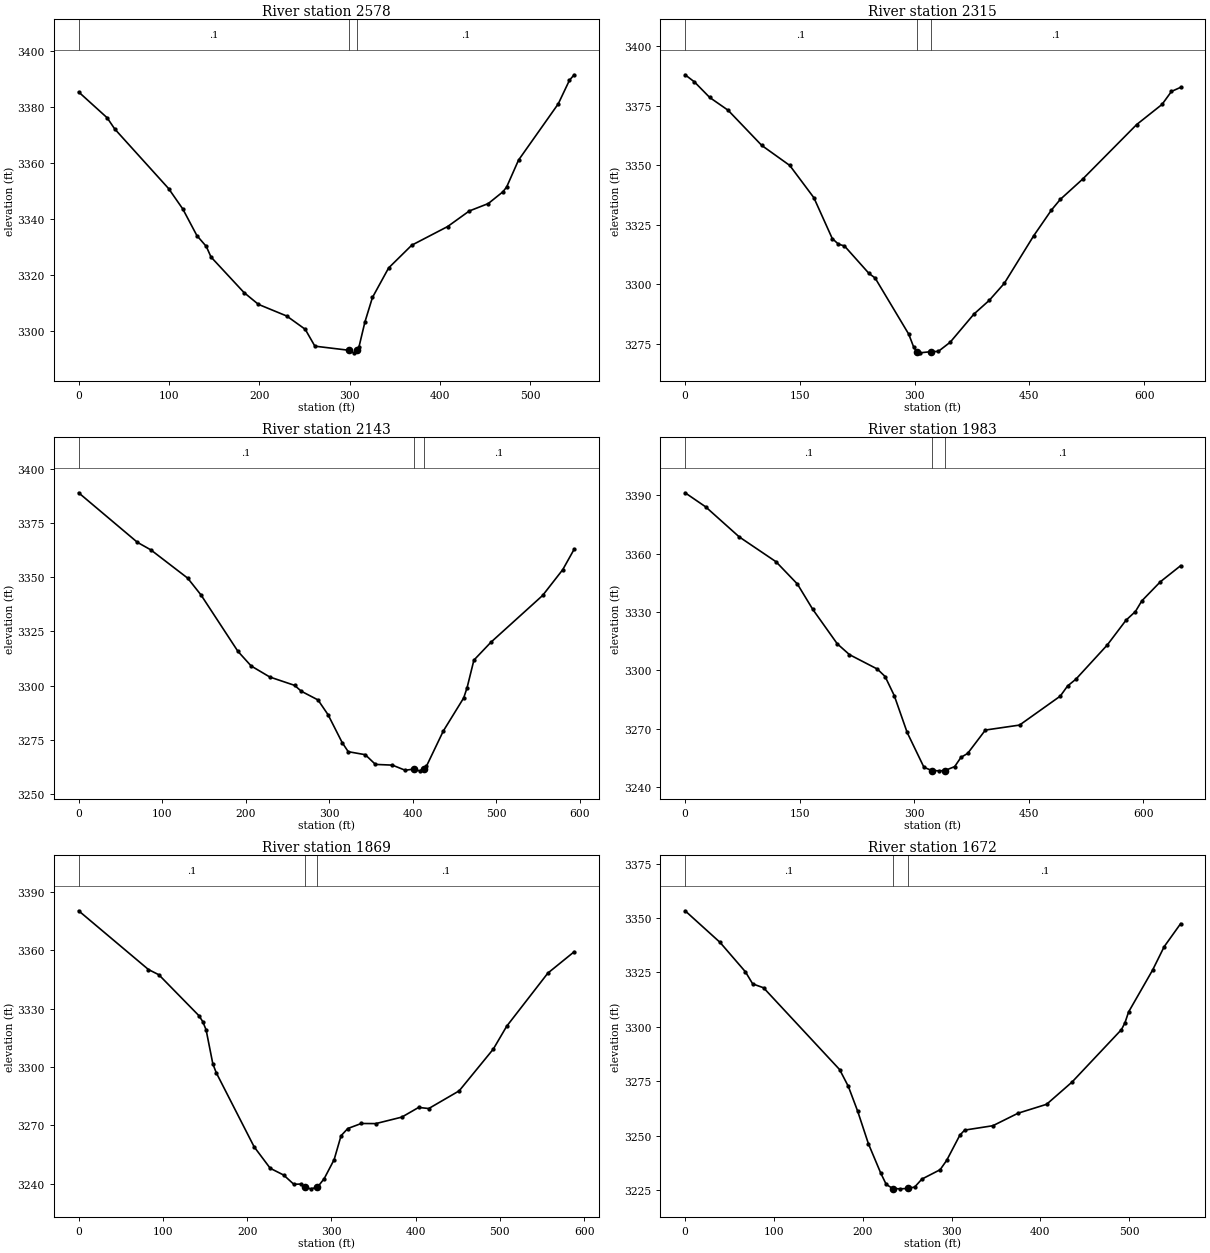
Type RM Length L Ch R = 1 ,2578    ,266.7,262.4,261
XS GIS Cut Line= 4
2306144.03721248638757.660041983 2305977.1184755638557.795934132
2305935.88637953638500.3796519512305723.07009656638545.004407034
#Sta/Elev= 30
       0  3385.4    31.5 3376.21      40 3372.18    99.6 3350.94   115.3 3343.66
   130.9 3334.17   141.3 3330.31   146.5 3326.54     183 3313.87     199 3309.64
   230.3 3305.49   250.8 3300.75   261.5 3294.73   298.8 3293.28   304.5 3292.35
  308.29 3293.27   310.4 3294.59   316.9 3303.38   325.2 3312.09   343.1 3322.62
   368.7 3330.74   408.4 3337.39   432.4 3342.95   453.4 3345.59   469.7 3349.81
   473.8 3351.53   486.9 3361.09   530.9 3381.17   543.3 3389.59   548.5 3391.53
#Mann= 3 ,0,0
       0      .1       0   298.8    .045       0  308.29      .1       0
Bank Sta=298.8,308.29
XS Rating Curve= 0 ,0
Exp/Cntr(USF)=0,0
Exp/Cntr=0.3,0.1

Type RM Length L Ch R = 1 ,2315    ,168.9,172.2,175.9
XS GIS Cut Line= 3
2306221.37148459638721.3854432392306227.92506546638456.404759679
2305950.56596301638192.921678619
#Sta/Elev= 30
       0 3387.92    12.2 3384.93    32.2 3378.39    56.2 3373.04   100.2 3358.28
   136.8 3349.88   168.3 3336.35   192.3 3319.23   200.3 3316.89   208.3  3316.1
   240.3 3304.59   248.3 3302.68   292.3 3279.09   298.8 3273.62  302.913271.732
   306.8 3271.28   320.9 3271.76   330.9 3271.88   346.4 3275.72   377.5 3287.55
   397.5  3293.3   417.1 3300.41   455.6  3320.4   478.8  3331.2   490.4 3335.67
   519.5 3344.14   590.2 3367.06   623.3 3375.49   635.6 3380.93   647.6 3382.65
#Mann= 3 ,-1,0
       0      .1       0  302.91    .045       0   320.9      .1       0
Bank Sta=302.91,320.9
XS Rating Curve= 0 ,0
Exp/Cntr(USF)=0,0
Exp/Cntr=0.3,0.1

Type RM Length L Ch R = 1 ,2143    ,154.4,160.1,165
XS GIS Cut Line= 3
2306307.50241529638703.5999999622306321.53559342638391.170517061
2306270.16957486638115.122919132
#Sta/Elev= 30
       0 3388.83    70.5 3365.99    86.5 3362.54   130.6 3349.53   146.6 3341.77
   190.7 3315.87   206.6  3309.1     229    3304   258.7 3300.16   266.7 3297.46
   286.7 3293.45   298.7 3286.67   315.6 3273.85   322.9 3269.63   343.3 3268.24
   355.5 3263.77   375.8 3263.44   391.1 3261.08401.52313261.614   408.3 3260.81
   413.5 3261.61   416.5 3262.88   436.8 3279.17   461.2 3294.39   465.3 3299.17
   473.4 3311.78   493.8 3320.02   555.7 3341.55   579.8 3353.43   593.5 3362.85
#Mann= 3 ,-1,0
       0      .1       0401.5231    .045       0   413.5      .1       0
Bank Sta=401.5231,413.5
XS Rating Curve= 0 ,0
Exp/Cntr(USF)=0,0
Exp/Cntr=0.3,0.1

Type RM Length L Ch R = 1 ,1983    ,119.8,114.3,107.6
XS GIS Cut Line= 4
2306328.55609357638711.9061840452306344.96511875638460.848098892
2306445.06017231638360.7530453342306389.26948672638111.335862698
#Sta/Elev= 30
       0 3391.27    26.8 3384.08    70.9  3368.6     119 3355.86     147 3344.41
   167.1 3331.41   199.2  3313.7   215.2 3308.13   251.6 3300.75   261.8 3296.91
   273.8 3287.11   290.7 3268.17   312.7 3250.27   323.1 3248.62   332.8 3248.46
  340.05 3248.61   352.9 3250.63   361.1 3255.37   369.9 3257.41   393.1 3269.41
   437.8 3271.96   491.1 3286.83   500.7 3292.05   511.6 3295.54   552.6 3313.07
   577.2 3325.83   589.5 3330.28   597.9 3335.76   622.2 3345.58   648.7 3353.82
#Mann= 3 ,-1,0
       0      .1       0   323.1    .045       0  340.05      .1       0
Bank Sta=323.1,340.05
XS Rating Curve= 0 ,0
Exp/Cntr(USF)=0,0
Exp/Cntr=0.3,0.1

Type RM Length L Ch R = 1 ,1869    ,198.1,196.9,195.8
XS GIS Cut Line= 3
2306495.92815034638692.215353837 2306520.5416881638239.326259051
2306499.20995538638106.413155146
#Sta/Elev= 30
       0 3380.19    82.9 3350.01    95.2 3347.34   142.7 3326.36   147.3  3323.3
   151.3 3319.06   159.3 3301.58   163.3 3297.07   208.3 3258.99   227.4 3247.96
   243.4 3244.47   255.4 3239.75   263.4 3239.84   269.1 3238.26   275.4  3237.4
   283.5 3238.24   291.5 3242.65   303.3 3252.42   311.5 3264.68   319.5 3268.38
   335.5 3270.96   352.7  3270.9   383.6 3274.23   403.6 3279.21   415.6 3278.64
   451.7 3287.72   492.2 3309.16   508.1  3320.9     557  3348.2   588.2 3359.14
#Mann= 3 ,-1,0
       0      .1       0   269.1    .045       0   283.5      .1       0
Bank Sta=269.1,283.5
XS Rating Curve= 0 ,0
Exp/Cntr(USF)=0,0
Exp/Cntr=0.3,0.1

Type RM Length L Ch R = 1 ,1672    ,150,152,149.1
XS GIS Cut Line= 3
2306666.52540593638671.7556639872306704.26616383638483.051874493
2306674.72991852638118.771515643
#Sta/Elev= 30
       0 3353.33    39.3 3338.83    67.9 3325.31    76.1 3319.75    88.3 3317.97
     174 3280.38   183.8 3272.65   194.3 3261.27   206.4 3246.31   220.2 3232.91
   226.4 3227.68   233.7 3225.77   242.4 3225.62   251.2 3225.81   258.5 3226.46
   266.6  3230.1   287.1  3234.4   294.5  3238.7   309.3 3250.24   314.7 3252.59
   346.5 3254.61   374.9 3260.36     407 3264.45   435.6 3274.65   491.3 3298.77
   495.3 3301.99   499.3 3306.86   526.3 3326.07   539.4 3336.87   557.9 3347.42
#Mann= 3 ,-1,0
       0      .1       0   233.7    .045       0   251.2      .1       0
Bank Sta=233.7,251.2
XS Rating Curve= 0 ,0
Exp/Cntr(USF)=0,0
Exp/Cntr=0.3,0.1

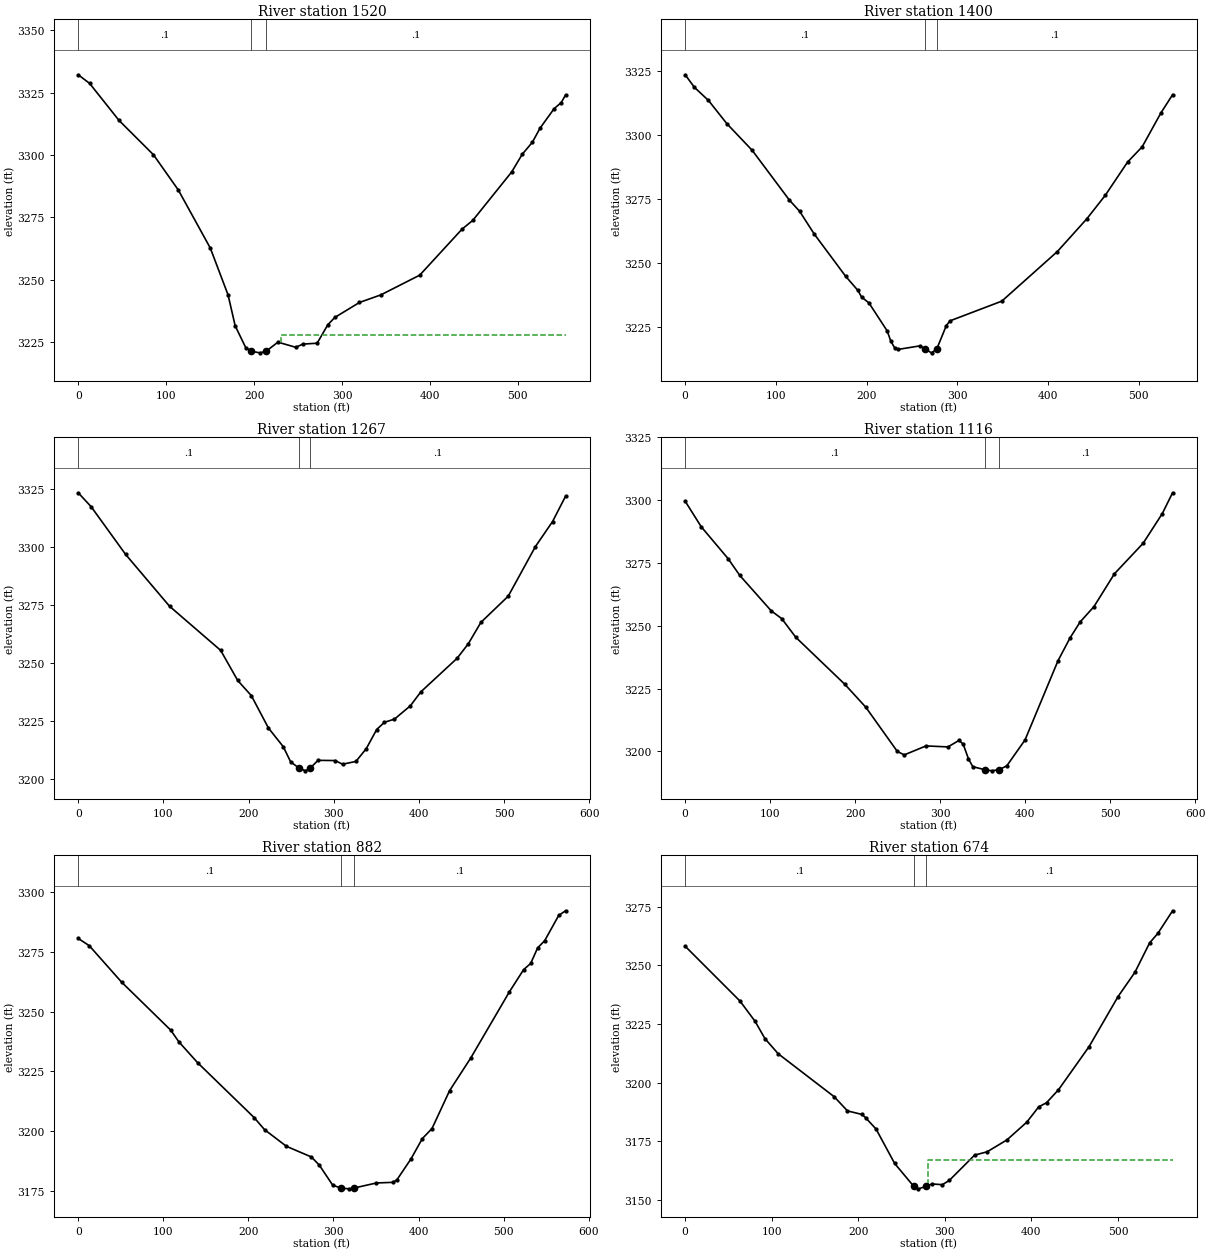
Type RM Length L Ch R = 1 ,1520    ,118.6,119.6,116.1
XS GIS Cut Line= 4
2306822.92155845638665.902322933 2306848.2802162638486.933434801
2306833.45548733638397.1130187052306803.59456297638116.199936023
#Sta/Elev= 30
       0 3332.13    12.9  3328.7    46.4 3313.86    85.6  3300.1   113.8 3286.02
   150.2 3262.77   170.4 3244.02   178.5 3231.63   190.6 3222.84  197.033221.431
   206.7 3220.82   213.7 3221.45   227.1  3225.1   247.4 3223.04   255.5 3224.32
   271.7 3224.67   283.8 3232.04   291.8 3234.99   319.8 3240.98   344.1 3244.01
   388.4 3251.92   436.6 3270.38   448.7 3273.84     493 3293.25     505 3300.33
   516.5 3305.12   525.1 3310.71   541.2 3318.56   549.3    3321   554.3 3324.08
#Mann= 3 ,-1,0
       0      .1       0  197.03    .045       0   213.7      .1       0
#XS Ineff= 2 , 0
                          230.68         3228.14
Permanent Ineff=
       F       F
Bank Sta=197.03,213.7
XS Rating Curve= 0 ,0
Exp/Cntr(USF)=0,0
Exp/Cntr=0.3,0.1

Type RM Length L Ch R = 1 ,1400    ,134.1,133.5,131.2
XS GIS Cut Line= 3
2306919.78773192638658.7258811212306942.46084667638434.610862318
2306881.41784544638128.523813291
#Sta/Elev= 30
       0 3323.47    10.2 3318.57    25.7 3313.45      46 3304.39    73.9    3294
   114.9  3274.6   126.2 3270.22   142.3 3261.36     177 3244.85   190.5 3239.35
   194.5 3236.78   202.6  3234.5   222.7  3223.6   226.7 3219.61   230.8 3217.07
   235.2 3216.39     259 3217.76  264.473216.513   271.6 3215.03  277.363216.515
   287.9 3225.63     292 3227.51   349.1 3235.19   410.3 3254.51   442.9 3267.32
   463.1 3276.42   487.8 3289.44   503.9 3295.39   524.5 3308.57   537.4  3315.7
#Mann= 3 ,-1,0
       0      .1       0  264.47    .045       0  277.36      .1       0
Bank Sta=264.47,277.36
XS Rating Curve= 0 ,0
Exp/Cntr(USF)=0,0
Exp/Cntr=0.3,0.1

Type RM Length L Ch R = 1 ,1267    ,153.6,151.3,148.3
XS GIS Cut Line= 4
2307065.32132386638664.3200110432307075.16673896638441.157268684
2306989.83980806638242.6080640862306986.55800303638109.694960181
#Sta/Elev= 30
       0 3323.26    15.2 3317.26    55.6 3296.76   107.2 3274.45   167.3 3255.44
   187.3 3242.49   203.3 3235.97   223.4 3222.03   240.8    3214   249.5 3207.45
   259.1 3204.86   266.9 3203.61  272.653204.867   281.6 3208.13   301.8 3208.03
   310.4 3206.46   326.1 3207.65   338.3 3213.17   350.5 3221.38   359.6  3224.5
   371.4 3225.87   390.1 3231.61   402.3 3237.57   444.9 3252.02   458.1 3258.28
   472.9 3267.49     505 3278.77   536.9  3300.1     557 3310.85   572.4 3321.83
#Mann= 3 ,-1,0
       0      .1       0   259.1    .045       0  272.65      .1       0
Bank Sta=259.1,272.65
XS Rating Curve= 0 ,0
Exp/Cntr(USF)=0,0
Exp/Cntr=0.3,0.1

Type RM Length L Ch R = 1 ,1116    ,222.7,233.3,240.6
XS GIS Cut Line= 4
2307165.41637742638631.5019606962307231.05247811638365.675752886
2307103.06208176638242.6080640862307089.93486162638121.181277802
#Sta/Elev= 30
       0 3299.54    18.9 3289.37    50.5 3276.69    64.2 3270.03   101.3  3255.9
   113.6 3252.83   130.1 3245.41   187.8  3226.7   212.5 3217.58   249.6 3199.97
   257.8  3198.6   283.4 3202.17   309.2 3201.77   322.2 3204.36   327.1 3202.89
   333.3 3197.05   338.4  3193.9   352.6 3192.71     361 3192.25   369.6 3192.76
   378.4 3194.23   399.9 3204.55   438.7 3236.08   452.8 3245.12   464.9 3251.57
     481  3257.6   505.1 3270.68   538.8 3282.78   561.4 3294.62   573.5  3302.9
#Mann= 3 ,-1,0
       0      .1       0   352.6    .045       0   369.6      .1       0
Bank Sta=352.6,369.6
XS Rating Curve= 0 ,0
Exp/Cntr(USF)=0,0
Exp/Cntr=0.3,0.1

Type RM Length L Ch R = 1 ,882     ,210.6,208.7,203.9
XS GIS Cut Line= 4
2307255.30285492638625.5258372262307328.84095274638403.519694017
2307371.50441819638264.0429800432307322.00927324638077.373975937
#Sta/Elev= 30
       0 3280.49      13 3277.46    50.9 3262.29   108.6 3242.27   118.3 3237.35
   140.2 3228.69   206.7 3205.77     219 3200.71   244.7 3193.77     274 3189.33
   283.3 3185.93   299.1 3177.55   308.9 3176.34   318.5 3176.03  323.773176.343
   350.5 3178.48   369.7 3178.74   374.4 3179.73     391 3188.48   404.4 3196.99
   415.8  3201.2   436.5 3217.03   461.3 3230.62   506.8 3258.27   523.4 3267.46
   531.7 3270.05   539.9 3276.54   548.2 3279.56   564.7 3290.11   572.8 3292.03
#Mann= 3 ,-1,0
       0      .1       0   308.9    .045       0  323.77      .1       0
Bank Sta=308.9,323.77
XS Rating Curve= 0 ,0
Exp/Cntr(USF)=0,0
Exp/Cntr=0.3,0.1

Type RM Length L Ch R = 1 ,674     ,71.3,67.9,63.8
BEGIN DESCRIPTION:
IFA needed to wet channel downstreasm
END DESCRIPTION:
XS GIS Cut Line= 3
2307576.46227231638615.7510319212307533.43716955638296.110263454
2307416.08427276638086.048278909
#Sta/Elev= 30
       0  3258.2    63.3 3234.84    80.8 3226.17    92.1 3218.85   107.5 3212.36
   172.1 3194.07   187.5 3188.01   204.4 3186.49   208.4 3185.11   220.5  3180.3
     242 3165.61   264.1 3155.84   269.3 3154.79   278.33155.823   285.1 3156.87
   297.2 3156.57   305.3 3158.43   334.4 3169.17   348.8 3170.57   371.7 3175.64
   394.6 3183.19   408.4 3189.72   417.5 3191.51   431.3 3197.02   466.7 3215.45
     500 3236.68   519.6 3247.09   536.6 3259.64   546.1 3263.68   563.1 3273.31
#Mann= 3 ,0,0
       0      .1       0   264.1    .045       0   278.3      .1       0
#XS Ineff= 2 , 0
                          281.06         3166.93
Permanent Ineff=
       F       F
Bank Sta=264.1,278.3
XS Rating Curve= 0 ,0
Exp/Cntr(USF)=0,0
Exp/Cntr=0.3,0.1

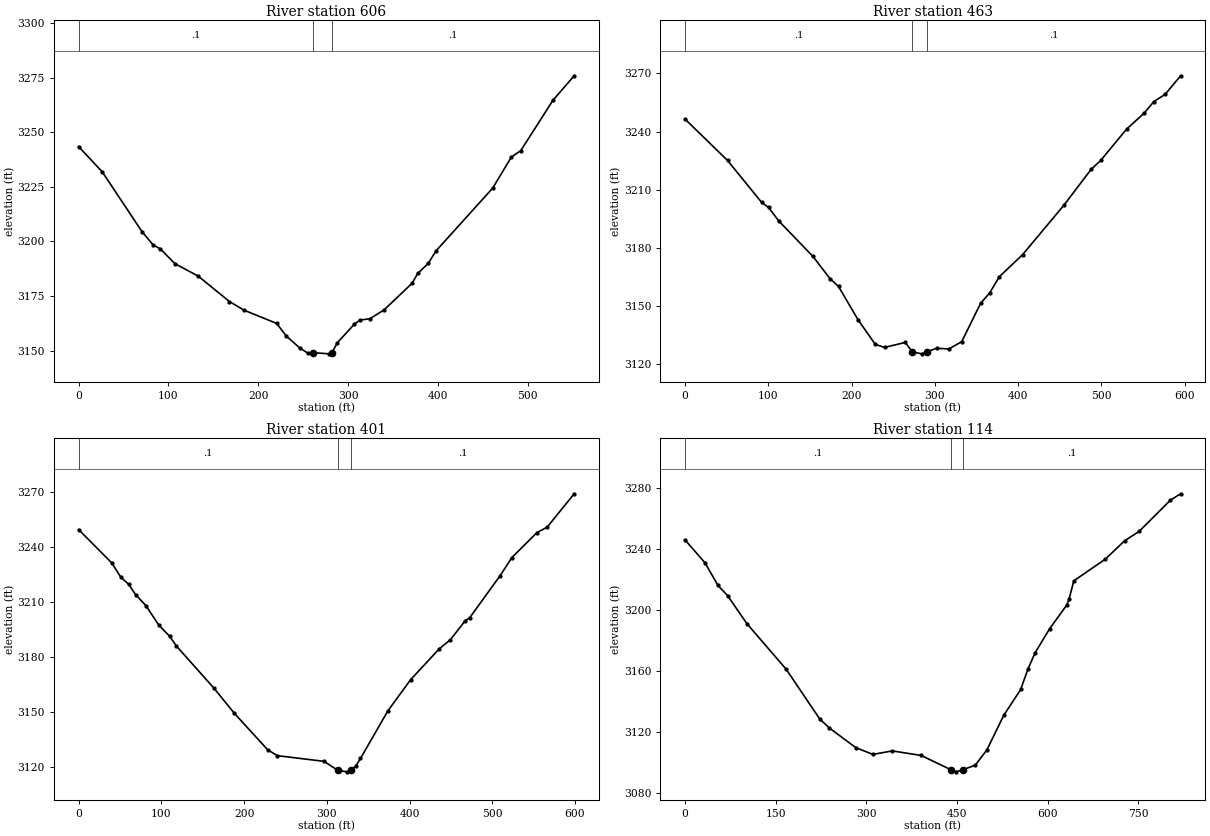
Type RM Length L Ch R = 1 ,606     ,140.3,143,141.8
XS GIS Cut Line= 4
 2307649.4094196638559.1972369282307615.25415776638332.207059266
2307542.66117903638249.5380925782307447.36576986638060.081743391
#Sta/Elev= 30
       0 3243.41    26.3 3231.84    70.8 3204.36    82.9 3198.45      91  3196.6
   107.2 3189.85     133 3184.19   167.9 3172.52   184.1 3168.58   220.5 3162.51
     231 3156.81   246.3 3151.25   254.9 3148.99  260.83 3149.14   279.2 3148.61
   282.1 3149.15   287.7 3153.56     307 3162.23   313.4 3164.07   324.1 3164.65
     340  3168.7   371.3 3180.94   377.4 3185.37   389.2 3189.98   397.8 3195.69
   460.9 3224.41   481.7 3238.62   492.2 3241.59     528 3264.59   551.6 3275.79
#Mann= 3 ,0,0
       0      .1       0  260.83    .045       0   282.1      .1       0
Bank Sta=260.83,282.1
XS Rating Curve= 0 ,0
Exp/Cntr(USF)=0,0
Exp/Cntr=0.3,0.1

Type RM Length L Ch R = 1 ,463     ,61.2,62.1,60.9
XS GIS Cut Line= 3
2307818.98582853638522.906933472 2307772.9290707638319.944949792
2307505.95599986 638039.70128771
#Sta/Elev= 30
       0 3246.42      51 3225.11      92 3203.47   100.2 3200.89   112.5 3193.93
   153.5 3175.67     174 3164.23   184.3 3160.14   207.7 3142.99   228.5 3130.28
   239.6 3128.73   264.4 3131.29   273.13126.364   284.6 3125.41   290.4 3126.38
     302 3128.28   316.9 3127.94   332.3 3131.71   354.9 3151.43   365.8 3156.82
   377.5 3165.21   405.3 3176.52     455 3202.06   487.6 3220.47   499.2 3225.15
   530.3 3241.29   551.4 3249.53     563 3255.47   576.6 3259.23   595.2 3268.79
#Mann= 3 ,-1,0
       0      .1       0   273.1    .045       0   290.4      .1       0
Bank Sta=273.1,290.4
XS Rating Curve= 0 ,0
Exp/Cntr(USF)=0,0
Exp/Cntr=0.3,0.1

Type RM Length L Ch R = 1 ,401     ,286.9,287.2,286.2
XS GIS Cut Line= 3
2307879.01842887638499.9882674732307828.59494884638295.745286856
2307561.29192877638013.674144125
#Sta/Elev= 30
       0 3249.69      40  3231.5    50.9 3223.78    60.6 3219.74    68.8 3214.21
    81.2 3208.21    97.2 3197.36     110 3191.43   118.3 3186.04   163.6 3163.07
   188.3 3149.32   228.4 3129.49   240.1 3126.24   296.6 3123.12   313.1 3118.26
   324.1 3117.39   329.6 3118.23   335.1 3120.67   340.7  3124.7   373.7  3150.6
   401.3 3167.72     436 3184.62   449.4 3189.53   466.9 3199.71   472.8  3201.6
   509.6 3224.58   523.7 3234.43   554.1 3248.08   566.2 3250.94     599 3269.24
#Mann= 3 ,-1,0
       0      .1       0   313.1    .045       0   329.6      .1       0
Bank Sta=313.1,329.6
XS Rating Curve= 0 ,0
Exp/Cntr(USF)=0,0
Exp/Cntr=0.3,0.1

Type RM Length L Ch R = 1 ,114     ,,,
XS GIS Cut Line= 4
2307993.32929485638447.3057135962307963.57411212638041.530861707
2307904.62174498637987.0196126472307571.38473672637986.112626016
#Sta/Elev= 30
       0 3245.95      33 3230.92    54.3 3216.14    70.3 3209.41   102.4 3190.93
   167.5 3160.95   222.7 3128.45   238.8 3122.43   282.9 3109.44     311 3105.09
   343.1 3107.37   390.6 3104.41  439.59 3095.11   448.6 3093.62   460.5 3095.09
   480.3 3097.97   499.6    3108   527.6  3130.8   555.6 3147.72   567.6 3161.18
   579.6 3171.95   603.6 3187.68   631.6 3203.05   635.6 3206.96   643.6 3219.14
   695.6 3233.32   727.6  3245.4   751.6 3251.56   803.6 3272.15   820.4  3276.3
#Mann= 3 ,0,0
       0      .1       0  439.59    .045       0   460.5      .1       0
Bank Sta=439.59,460.5
XS Rating Curve= 0 ,0
Exp/Cntr(USF)=0,0
Exp/Cntr=0.3,0.1
LCMann Table=0

Chan Stop Cuts=-1
Use User Specified Reach Order=0
Composite Channel Slope=5